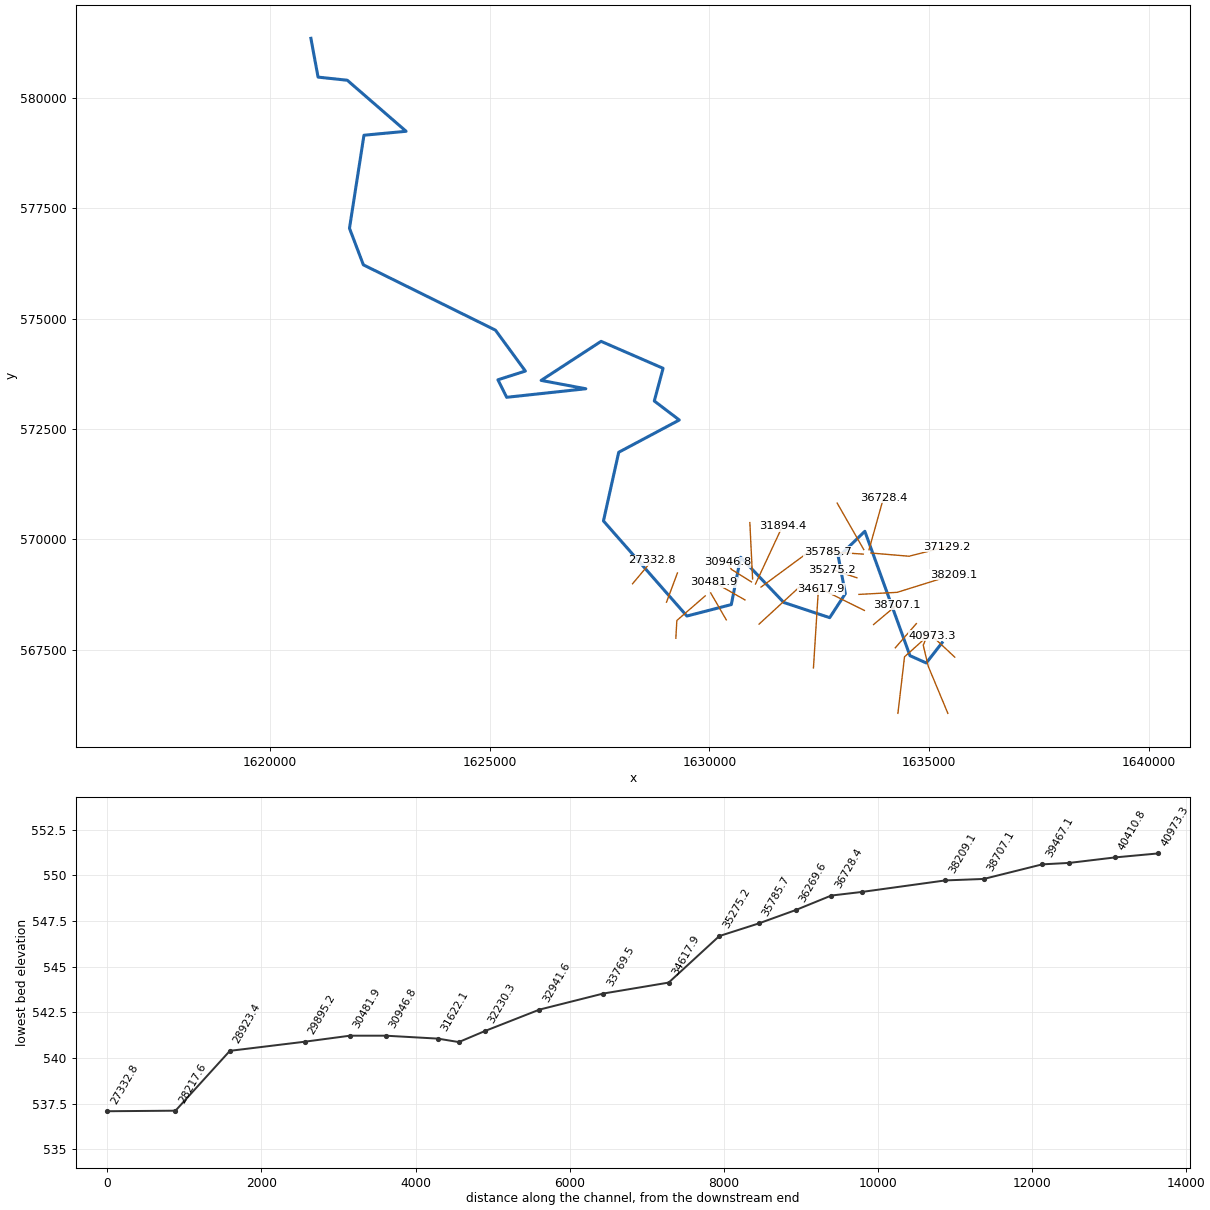
--- GuyanCr.prj (project) ---

Proj Title=GuyanCr
Current Plan=p01
Geom File=g01
Flow File=f01
Plan File=p01
DSS Export Rating Curves=0
DSS Export Rating Curve Sorted=0
DSS Export Volume Flow Curves=0
DXF OffsetX=0
DXF OffsetY=0
DXF ScaleX=0
DXF ScaleY=0

--- GuyanCr.p01 (plan) ---

Plan Title=Floodplain
Program Version=4.00
Geom File=g01
Flow File=f01
K Sum by GR=0
Std Step Tol=0.01
Critical Tol=0.01
Num of Std Step Trials=20
Max Error Tol=0.3
Flow Tol Ratio=0.001
Split Flow NTrial=30
Split Flow Tol=0.02
Split Flow Ratio=0.02
Log Output Level=0
Friction Slope Method=1
Unsteady Friction Slope Method=2
Unsteady Bridges Friction Slope Method=1
Global Log Level=0
CheckData=False
Run HTab=0
Run UNet=0
Run PostProcess=0
UNET Theta=0
UNET Theta Warmup=0
UNET ZTol=0
UNET ZSATol=0
UNET MxIter=0
UNET MaxInSteps=0
UNET DtIC=0
UNET DtMin=0
UNET MaxCRTS=0
UNET WFStab=0
UNET SFStab=0
UNET WFX=0
UNET SFX=0
UNET DSS MLevel=0
UNET DZMax Abort=0
UNET Convert EG Bridges=0
UNET Use Existing IB Tables=0
UNET Froude Limit=0
UNET Froude Power=0
Write IC File=0
Echo Input=False
Echo Output=False
Write Detailed=0

--- GuyanCr.f01 (steady flow) ---

Flow Title=NFF Regression Equation
Program Version=4.10
Number of Profiles= 1
Profile Names=P100yr
River Rch & RM=GuyanCr,Main            ,40973.3
    4599
River Rch & RM=GuyanCr,Main            ,40410.8
    4602
River Rch & RM=GuyanCr,Main            ,39819.3
    5681
River Rch & RM=GuyanCr,Main            ,37129.2
    5694
River Rch & RM=GuyanCr,Main            ,36728.4
    5853
River Rch & RM=GuyanCr,Main            ,34617.9
    5891
River Rch & RM=GuyanCr,Main            ,32941.6
    5901
River Rch & RM=GuyanCr,Main            ,28923.4
    5962
Boundary for River Rch & Prof#=GuyanCr,Main            , 1
Up Type= 0
Dn Type= 3
Dn Slope=0.0022
DSS Import GetInterval= 0
DSS Import GetPeak= 0
DSS Import FillOption= 0

--- GuyanCr.g01 (geometry) ---

Geom Title=USGS 10m DEM
Program Version=4.10

River Reach=GuyanCr         ,Main
Reach XY= 30
      1635297.54      567662.013      1634936.87      567202.563
     1634565.695      567367.681     1633538.658      570185.128
     1632935.636      569603.107     1633095.097       568773.14
     1632738.708      568228.655     1631694.056      568572.619
      1630712.98      569596.596     1630498.944      568524.814
     1629488.326      568265.327      1627589.26      570419.307
     1627936.268        571974.6     1629315.301      572705.602
     1628746.139      573136.421     1628946.286      573877.064
     1627534.823      574487.414     1626170.618      573602.567
     1627187.702      573413.524     1625385.689      573219.911
     1625186.673      573616.595     1625811.658      573814.196
     1625130.668      574741.279     1622124.493      576220.142
     1621807.927      577048.331      1622137.64       579156.03
     1623096.652      579245.321     1621757.804      580401.552
     1621092.857      580472.478     1620929.871      581350.829

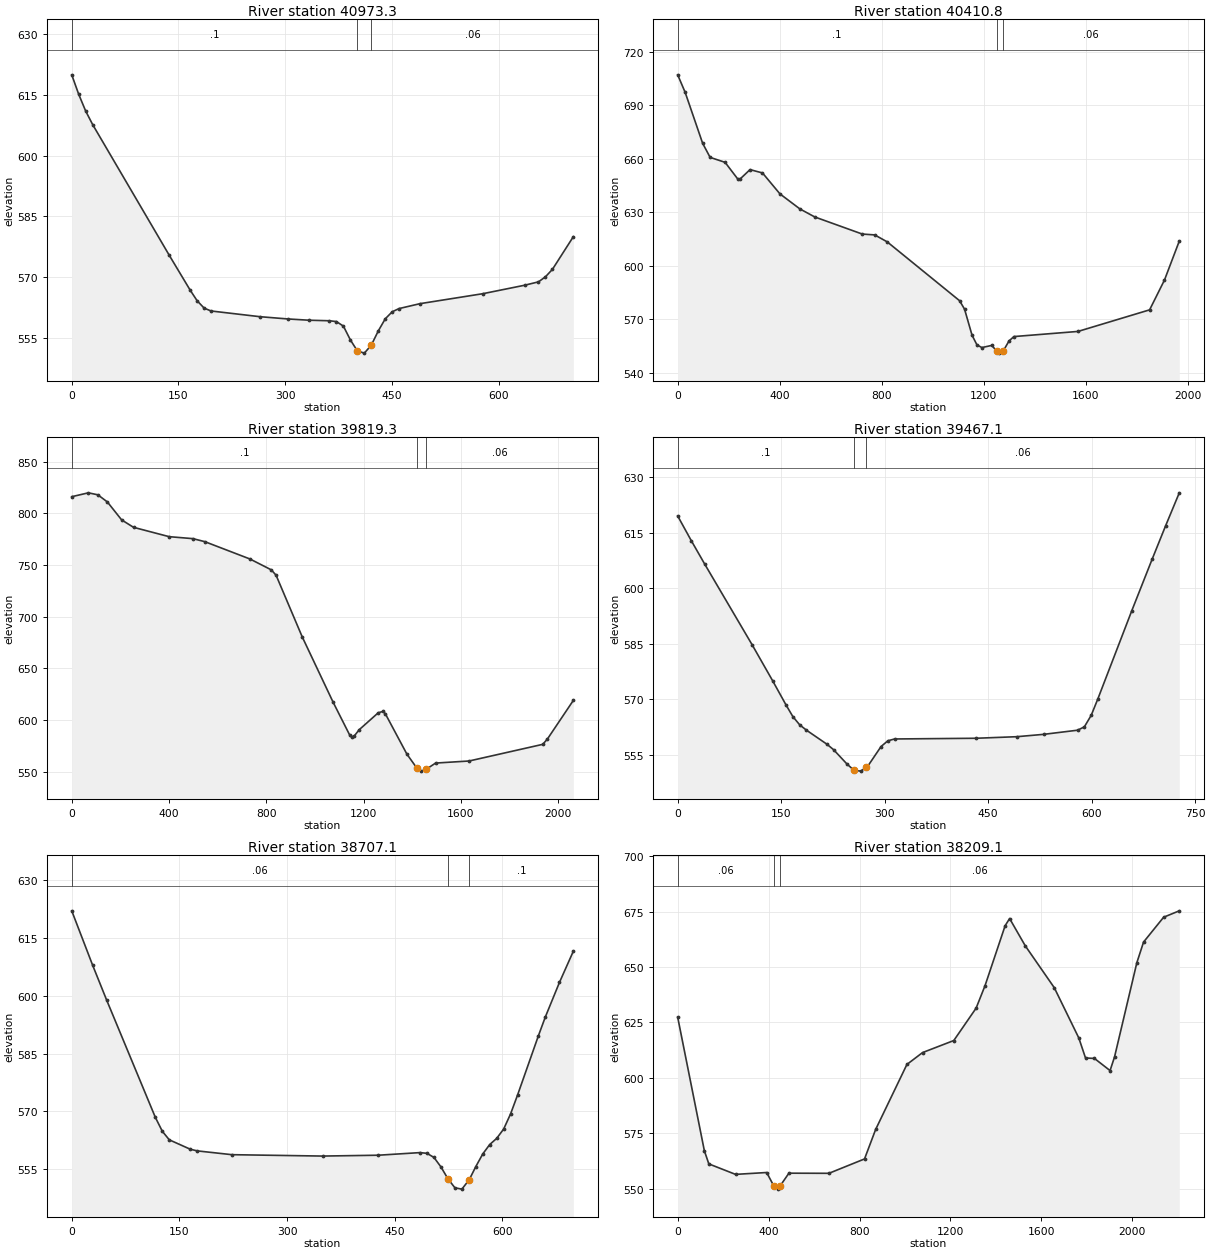
Type RM Length L Ch R = 1 ,40973.3 ,586.9,562.4,547.9
XS GIS Cut Line= 2
     1635585.075      567334.666     1635068.881      567814.944
#Sta/Elev= 30
       0  620.01     9.8  615.19    19.6  611.05    29.4  607.71   137.1  575.39
   166.5  566.77   176.3  564.15   186.1  562.34   195.8  561.63   264.4  560.22
   303.6  559.66     333  559.35   362.3  559.21   372.1  559.01   381.9  557.88
   391.7  554.47   401.5  551.76   411.3  551.21   421.1  553.18   430.9   556.7
   440.7  559.69   450.5  561.44   460.2  562.23   489.6  563.44   577.8   565.9
   636.5  567.99   656.1  568.83   665.9  570.08   675.7  571.92   705.1     580
#Mann= 3 , 0 , 0
       0      .1       0   401.5    .045       0   421.1     .06       0
Bank Sta=401.5,421.1
XS Rating Curve= 0 ,0
Exp/Cntr=0.3,0.1

Type RM Length L Ch R = 1 ,40410.8 ,605.1,591.5,563.6
XS GIS Cut Line= 4
     1635428.707      566060.608     1634982.511      567125.242
     1634867.928      567604.409     1634987.719      567901.284
#Sta/Elev= 30
       0  707.12    29.4  697.25    97.8  668.73   127.2   660.8   185.9  658.03
   234.8  648.82   244.6  648.66   283.7  653.94   332.6  652.08   401.1  640.32
   479.4  631.88     538  627.36   723.9  617.79   772.8  617.31   821.7  613.41
  1105.4  580.41    1125  575.67  1154.4  561.05  1173.7   555.6    1193  554.11
  1231.6  555.32    1251  552.19  1260.6  550.99  1275.9  551.97  1299.3   557.8
  1318.6  560.28  1569.8  563.16  1850.8  575.27    1909  591.95  1967.2  613.85
#Mann= 3 , 0 , 0
       0      .1       0    1251    .045       0  1275.9     .06       0
Bank Sta=1251,1275.9
XS Rating Curve= 0 ,0
Exp/Cntr=0.3,0.1

Type RM Length L Ch R = 1 ,39819.3 ,350.5,352.2,354
XS GIS Cut Line= 4
     1634291.554      566060.608     1634441.942      567341.665
     1634852.303      567708.575     1634930.428      567916.909
#Sta/Elev= 30
       0  816.15    68.4  819.89   107.5  817.96   146.6  811.04   205.2   793.7
   254.1  786.52   400.6  777.48   498.4  775.57   547.2  772.66   732.9  755.89
   820.8  745.37   840.4  740.15   947.8  680.57  1074.9  617.35  1143.3  585.46
    1153  583.52  1162.8     585  1182.4   590.8  1260.5  607.14  1280.1  608.47
  1289.8  606.12  1378.3  567.14    1420  553.36  1437.3  550.69    1457  552.36
  1496.3  558.49  1633.9  560.48  1937.1  576.61  1956.4  581.84  2062.8  619.11
#Mann= 3 , 0 , 0
       0      .1       0    1420    .045       0    1457     .06       0
Bank Sta=1420,1457
XS Rating Curve= 0 ,0
Exp/Cntr=0.3,0.1

Type RM Length L Ch R = 1 ,39467.1 ,762.9,759.9,755.9
XS GIS Cut Line= 2
     1634232.511      567547.117     1634711.678      568093.992
#Sta/Elev= 30
       0  619.56    19.6  612.92    39.3  606.51   108.1  584.69   137.6  575.04
   157.2  568.44     167  565.33   176.9  563.11   186.7  561.67   216.2   557.9
     226   556.4   245.6  552.49   255.5  550.86   265.3  550.61   273.3   551.6
   275.1  551.82   294.8  557.26   304.6   558.8   314.4   559.3   432.3  559.49
   491.3  559.91   530.6  560.55   579.7  561.67   589.5  562.58   599.4  565.68
   609.2   570.2   658.3  593.98   687.8   607.9   707.4  616.96   727.1  625.81
#Mann= 3 , 0 , 0
       0      .1       0   255.5    .045       0   273.3     .06       0
Bank Sta=255.5,273.3
XS Rating Curve= 0 ,0
Exp/Cntr=0.3,0.1

Type RM Length L Ch R = 1 ,38707.1 ,511.1,498,482.2
XS GIS Cut Line= 2
     1633737.719      568073.159     1634274.178      568521.075
#Sta/Elev= 30
       0  622.12    29.1  607.99    48.5  598.99   116.5  568.45   126.2  564.84
   135.9  562.62     165  560.19   174.7  559.75   223.2  558.76   349.4   558.4
   427.1  558.62   485.3   559.3     495  559.11   504.7  558.04   514.4  555.59
   524.2  552.48   533.9  550.15   543.6  549.81   553.9  552.28     563  555.67
   572.7  558.95   582.4   561.4   592.1     563   601.8  565.42   611.5  569.38
   621.2  574.27   650.3   589.7     660   594.6   679.5   603.5   698.9  611.63
#Mann= 3 , 0 , 0
       0     .06       0   524.2    .045       0   553.9      .1       0
Bank Sta=524.2,553.9
XS Rating Curve= 0 ,0
Exp/Cntr=0.3,0.1

Type RM Length L Ch R = 1 ,38209.1 ,1082.9,1079.9,1077
XS GIS Cut Line= 3
     1633404.386       568755.45     1634274.178      568802.325
     1635550.219      569198.159
#Sta/Elev= 30
       0  627.36   117.4  567.04     137  561.12   254.5  556.39   391.5  557.23
   423.2  551.11   440.4  549.73   450.2   551.1   489.4  556.93   665.5  556.87
   822.1  563.36     871  576.66  1008.6  606.02  1077.4  611.38  1214.9  616.82
  1313.1  631.44  1352.4   641.6  1440.8  668.66  1460.5   671.9  1529.2  659.61
    1657  640.68    1765  617.98  1794.5  608.94  1833.8  608.74  1902.5  603.25
  1922.2  609.42  2020.4  651.97  2049.9  661.28  2138.3   672.5  2207.1  675.38
#Mann= 3 , 0 , 0
       0     .06       0   423.2    .045       0   450.2     .06       0
Bank Sta=423.2,450.2
XS Rating Curve= 0 ,0
Exp/Cntr=0.3,0.1

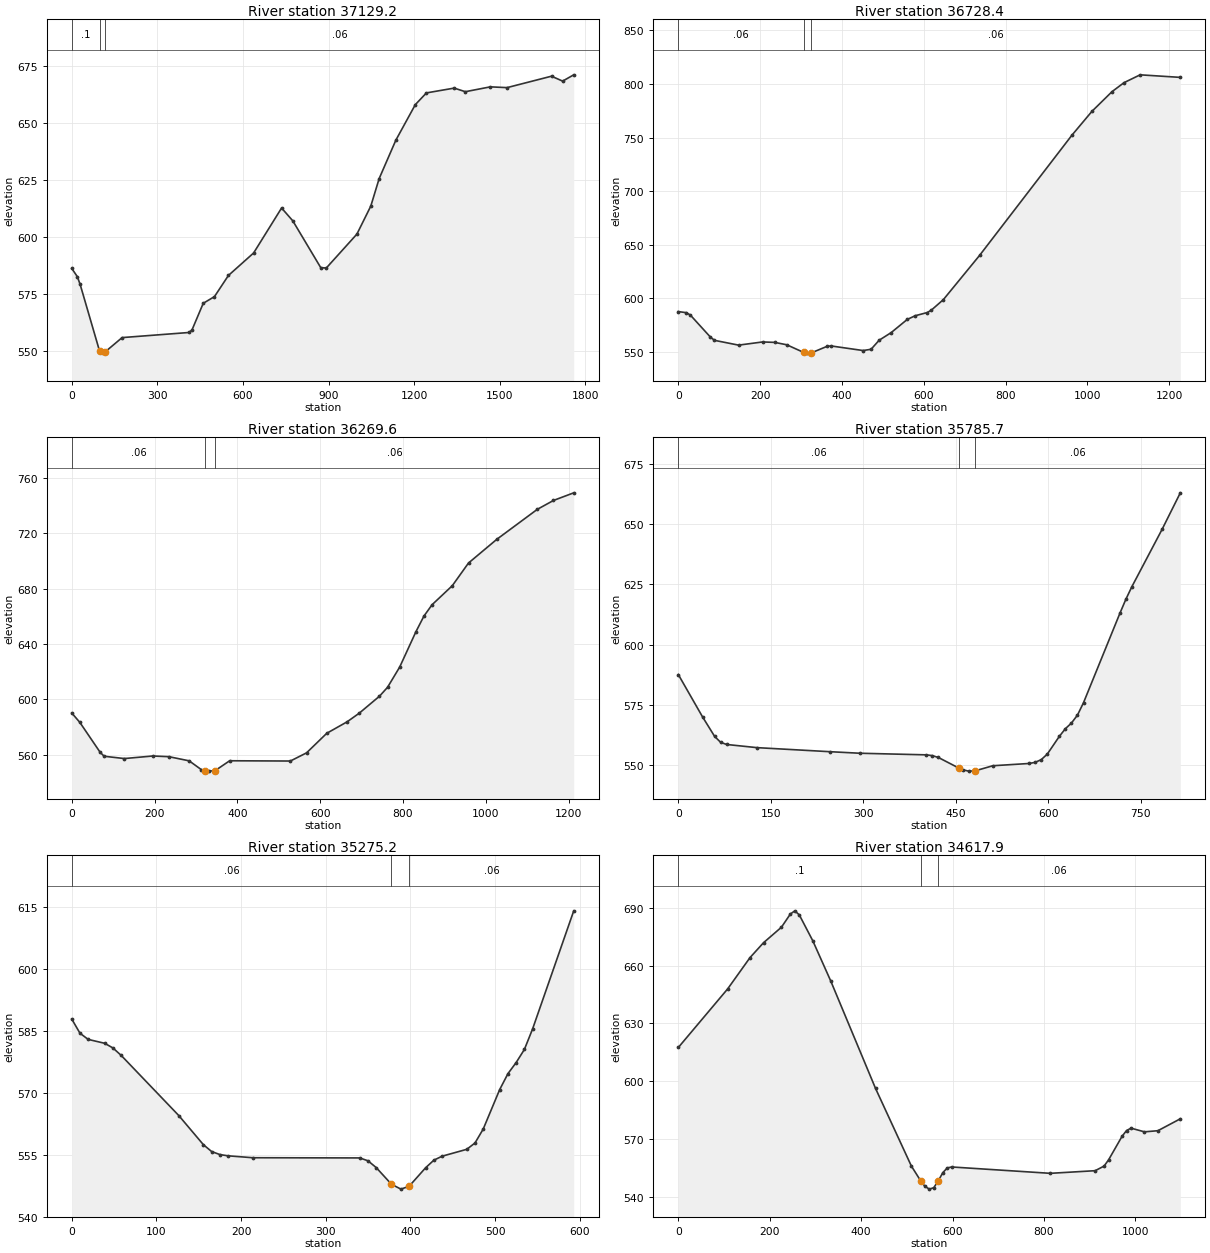
Type RM Length L Ch R = 1 ,37129.2 ,366.8,400.8,434.8
XS GIS Cut Line= 3
     1633675.219       569692.95     1634545.011      569620.034
     1635404.386      569838.784
#Sta/Elev= 30
       0  586.29    19.6  582.66    29.4  579.26    97.6  549.94   107.9   549.1
   117.7  549.72   176.5  555.92   411.9  558.17   421.7  559.35   460.9  570.99
   500.2  573.91   549.2  583.21   637.5  593.08   735.5  612.82   774.8  607.19
   872.8  586.63   892.3  586.48   999.5  601.36  1048.2  613.66  1077.5  625.74
    1136   642.6  1204.2   658.2  1243.2  663.36  1340.6  665.47  1379.6  663.89
  1467.3  666.02  1525.8  665.68  1681.7   670.7  1720.6  668.54  1759.6   671.3
#Mann= 3 , 0 , 0
       0      .1       0    97.6    .045       0   117.7     .06       0
Bank Sta=97.6,117.7
XS Rating Curve= 0 ,0
Exp/Cntr=0.3,0.1

Type RM Length L Ch R = 1 ,36728.4 ,441.6,458.8,475.1
XS GIS Cut Line= 2
     1633633.553      569765.867      1633965.22      570947.372
#Sta/Elev= 30
       0  587.65    19.6  586.65    29.4  584.42    78.5  563.82    88.4  560.83
   147.3  556.36   206.2  559.34   235.6  558.92   265.1  556.69   306.5  549.54
   314.2   548.9     324  548.97   363.2  555.17   373.1  555.62   451.6  551.32
   471.2  552.49   490.9  560.93   520.3  568.04   559.6  580.34   579.2  583.81
   608.7  586.79   618.5  589.01     648  598.87   736.3  640.02   962.1  752.23
  1011.2  774.55  1060.3  792.93  1089.7  801.33    1129  808.61  1227.2  806.23
#Mann= 3 , 0 , 0
       0     .06       0   306.5    .045       0     324     .06       0
Bank Sta=306.5,324
XS Rating Curve= 0 ,0
Exp/Cntr=0.3,0.1

Type RM Length L Ch R = 1 ,36269.6 ,454.2,484,509.5
XS GIS Cut Line= 2
     1633513.761      569771.075     1632909.664      570822.372
#Sta/Elev= 30
       0  590.13    19.6   583.3    68.4  561.78    78.2  558.86   127.1   557.2
   195.6  559.04   234.7  558.55   283.6  555.54   312.9   549.2   322.7  548.33
   332.5  548.11   346.6  548.54   381.4   555.6     528  555.41   567.1  561.31
     616  575.47   664.9  583.72   694.2  589.94   743.2  602.24   762.7  608.67
     792  623.27   831.2   648.8   850.7  660.19   870.3  668.37   919.2  682.14
   958.3  698.52  1026.7  715.66  1124.5  737.32  1163.6  743.74  1212.5  749.25
#Mann= 3 , 0 , 0
       0     .06       0   322.7    .045       0   346.6     .06       0
Bank Sta=322.7,346.6
XS Rating Curve= 0 ,0
Exp/Cntr=0.3,0.1

Type RM Length L Ch R = 1 ,35785.7 ,522.9,510.4,501.7
XS GIS Cut Line= 2
     1633504.646      569668.211     1632692.146      569720.294
#Sta/Elev= 30
       0  587.52    39.2  569.96    58.9   561.8    68.7  559.33    78.5  558.45
   127.5  557.14   245.2  555.46   294.3  554.81   402.2  554.14     412  553.82
   421.8  553.04   454.5  548.71     461  547.95   470.8  547.37   480.6  547.43
   510.1  549.61   568.9  550.55   578.8  551.03   588.6  552.14   598.4  554.44
     618  561.83   627.8  565.02   637.6  567.36   647.4  570.68   657.2  575.84
   716.1  612.95   725.9  618.86   735.7  624.12   784.7  647.97   814.2  663.12
#Mann= 3 , 0 , 0
       0     .06       0   454.5    .045       0   480.6     .06       0
Bank Sta=454.5,480.6
XS Rating Curve= 0 ,0
Exp/Cntr=0.3,0.1

Type RM Length L Ch R = 1 ,35275.2 ,676.5,657.3,677
XS GIS Cut Line= 2
     1633358.813      569131.752     1632796.313      569319.252
#Sta/Elev= 30
       0  587.89     9.7  584.46    19.4  582.96    38.9  582.02    48.6  580.89
    58.3   579.1   126.4  564.51   155.5  557.44   165.2  555.79     175  555.05
   184.7  554.75   213.8  554.29   340.2  554.24   349.9  553.54   359.6   551.9
   377.6  547.86   388.8  546.68   398.5  547.38     418  551.87   427.7   553.7
   437.4  554.66   466.6  556.33   476.3  557.87     486  561.25   505.4  570.79
   515.2  574.67   524.9  577.36   534.6  580.53   544.3   585.5   592.9  614.12
#Mann= 3 , 0 , 0
       0     .06       0   377.6    .045       0   398.5     .06       0
Bank Sta=377.6,398.5
XS Rating Curve= 0 ,0
Exp/Cntr=0.3,0.1

Type RM Length L Ch R = 1 ,34617.9 ,873.7,848.4,822.4
XS GIS Cut Line= 2
      1633527.72      568391.816     1632542.422      568877.448
#Sta/Elev= 30
       0  617.54   107.9  647.88   156.9  664.13   186.4  671.82   225.6  679.85
   245.2  686.71     255  688.35   264.8   686.2   294.2  672.84   333.5     652
   431.5  596.34     510  556.07   530.9  548.22   539.4  545.63   549.2  544.13
     559  544.88   568.8   548.4   578.7  552.64   588.5  555.11   598.3  555.61
     814  552.32   912.1  553.68   931.7  556.08   941.6  559.33     971   571.5
   980.8  574.48   990.6  575.73    1020  573.82  1049.4   574.4  1098.5  580.57
#Mann= 3 , 0 , 0
       0      .1       0   530.9    .045       0   568.8     .06       0
Bank Sta=530.9,568.8
XS Rating Curve= 0 ,0
Exp/Cntr=0.3,0.1

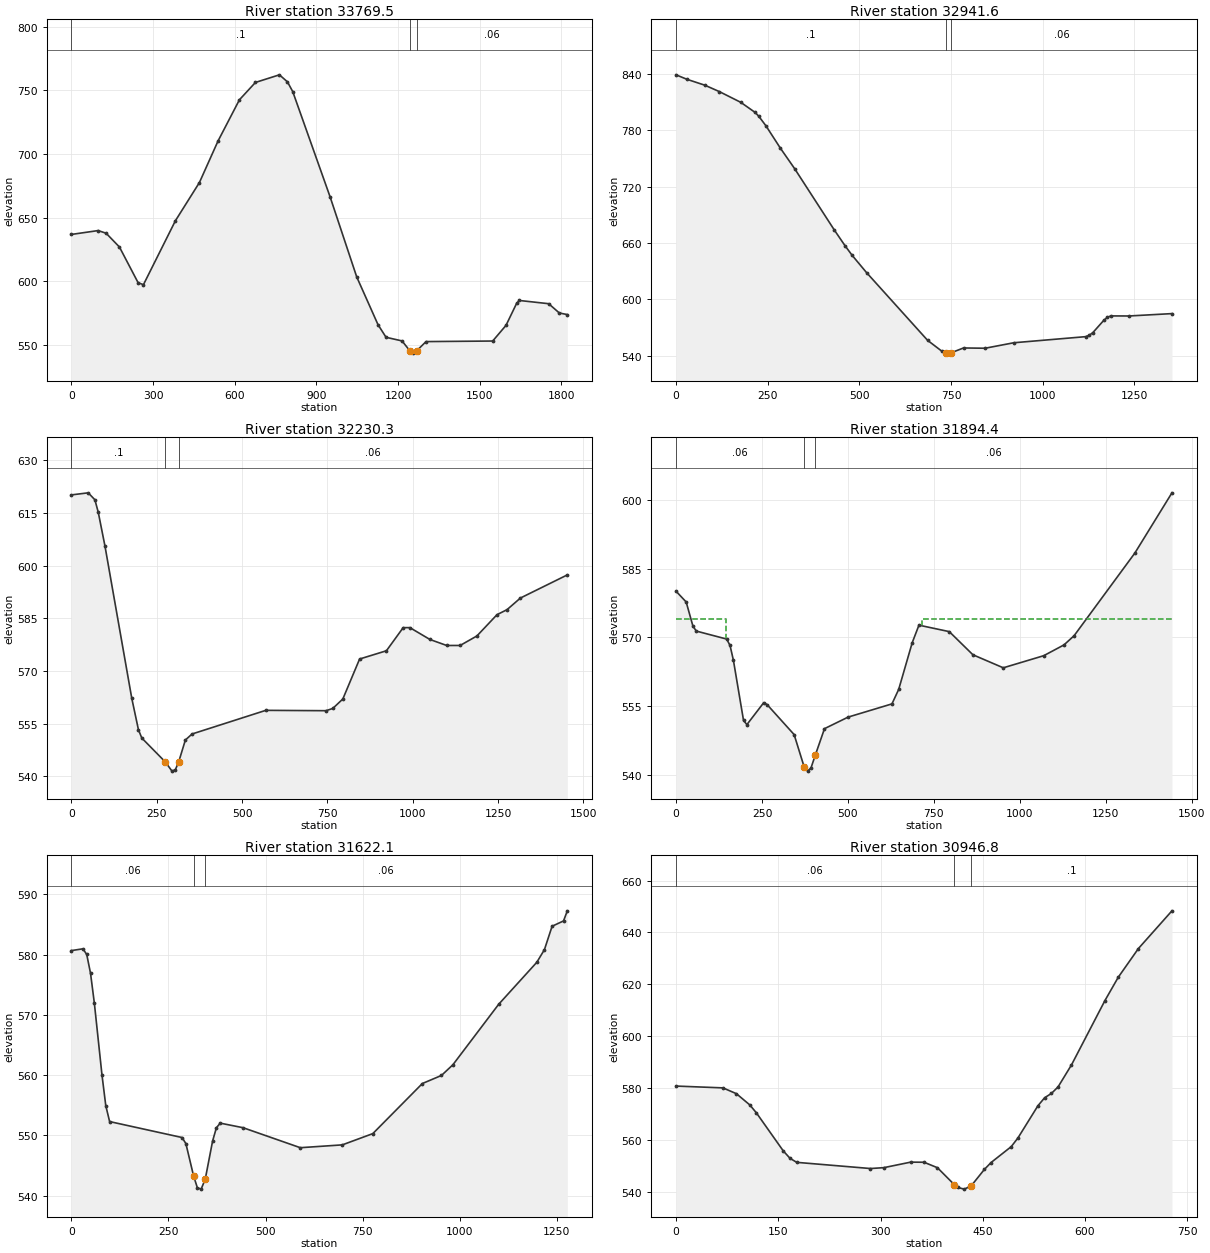
Type RM Length L Ch R = 1 ,33769.5 ,847.4,827.8,807.5
XS GIS Cut Line= 2
     1632368.811      567089.254     1632483.813      568907.794
#Sta/Elev= 30
       0  636.83      98  639.86   127.4  637.77   176.3  626.94   244.9  598.89
   264.5  597.34   382.1  647.64   470.2  677.62   538.8  710.36   617.2  742.66
     676  756.29   764.1  762.28   793.5   756.8   813.1  749.11   950.3  666.42
  1048.2  603.45  1126.6  565.83    1156  555.98  1214.8  553.12  1244.2  545.15
    1254  543.53  1268.4  545.34    1303   552.6  1547.9  553.04  1596.8  565.36
    1636  582.72  1645.8  584.92  1753.6  582.38  1792.8  575.07  1822.2  573.83
#Mann= 3 , 0 , 0
       0      .1       0  1244.2    .045       0  1268.4     .06       0
Bank Sta=1244.2,1268.4
XS Rating Curve= 0 ,0
Exp/Cntr=0.3,0.1

Type RM Length L Ch R = 1 ,32941.6 ,712.5,711.4,706
XS GIS Cut Line= 2
     1631131.832      568083.178     1632129.646      568996.336
#Sta/Elev= 30
       0  839.06    29.4  834.33    78.4  828.02   117.6  821.28   176.4  809.79
   215.6  799.02   225.4  795.01     245  784.84   284.2  761.13   323.4  739.12
   431.3  673.99   460.7  657.14   480.3   646.8   519.5  628.44   686.1  556.27
   725.3   544.6   736.2  542.69   744.9  542.65   751.2  543.18   784.1  548.15
   842.9  547.86   921.3   553.7  1117.4   560.2  1127.2  561.69    1137  564.56
  1166.4  577.45  1176.2  580.73    1186  582.29    1235  582.21  1352.6  584.74
#Mann= 3 , 0 , 0
       0      .1       0   736.2    .045       0   751.2     .06       0
Bank Sta=736.2,751.2
XS Rating Curve= 0 ,0
Exp/Cntr=0.3,0.1

Type RM Length L Ch R = 1 ,32230.3 ,324.6,335.9,346.9
XS GIS Cut Line= 2
     1631175.235      568920.851      1632347.11      569780.226
#Sta/Elev= 30
       0  620.14    49.1  620.73    68.7  618.75    78.6  615.16    98.2  605.57
   176.7  562.23   196.4  553.21   206.2  550.89   274.9   544.1   294.6  541.47
   304.4  541.86   314.2  544.08   333.8  550.33   353.5  552.05   569.5  558.78
   746.2  558.68   765.9  559.33   795.3  562.02   844.4   573.4     923  575.75
   972.1  582.33   991.7  582.34  1050.6  578.96  1099.7  577.25    1139  577.26
  1188.1  579.96    1247  586.02  1276.5  587.46  1315.7  590.77  1453.2  597.36
#Mann= 3 , 0 , 0
       0      .1       0   274.9    .045       0   314.2     .06       0
Bank Sta=274.9,314.2
XS Rating Curve= 0 ,0
Exp/Cntr=0.3,0.1

Type RM Length L Ch R = 1 ,31894.4 ,260.3,272.3,284.4
XS GIS Cut Line= 2
     1631049.367      568990.296     1631661.346      570296.719
#Sta/Elev= 30
       0  580.06    29.4  577.72    49.1  572.45    58.9  571.38   147.2  569.64
     157  568.25   166.8  565.03   196.3   551.9   206.1  551.01   255.2   555.8
     265  555.35   343.5  548.83   372.9  541.73   382.8  540.87   392.6  541.58
   404.8  544.29   431.8  550.12   500.5  552.64   628.1  555.52   647.7  558.68
     687  568.84   706.6  572.67   794.9  571.26   863.6  566.22     952  563.38
  1069.7  566.02  1128.6  568.37    1158  570.37  1334.7  588.37  1442.7   601.5
#Mann= 3 , 0 , 0
       0     .06       0   372.9    .045       0   404.8     .06       0
#XS Ineff= 2 , 0
          146.48  574.08  716.62          573.99
Permanent Ineff=
       F       F
Bank Sta=372.9,404.8
XS Rating Curve= 0 ,0
Exp/Cntr=0.3,0.1

Type RM Length L Ch R = 1 ,31622.1 ,651.4,675.3,698.1
XS GIS Cut Line= 2
     1630983.813      569105.711     1630921.313      570381.752
#Sta/Elev= 30
       0  580.68    29.5  580.97    39.3  580.04    49.1  576.92      59  571.94
    78.6  560.04    88.4  554.93    98.3  552.28     285  549.63   294.8  548.62
   314.5  543.29   324.3   541.3   334.1  541.06   344.7  542.72   363.6  549.04
   373.4  551.25   383.3  552.02   442.2  551.26   589.6  547.94   697.8  548.41
   776.4  550.28   904.1   558.6   953.3  559.94   982.8  561.72  1100.7  571.76
    1199  578.74  1218.6  580.84  1238.3  584.72  1267.7   585.6  1277.6  587.28
#Mann= 3 , 0 , 0
       0     .06       0   314.5    .045       0   344.7     .06       0
Bank Sta=314.5,344.7
XS Rating Curve= 0 ,0
Exp/Cntr=0.3,0.1

Type RM Length L Ch R = 1 ,30946.8 ,464.1,464.9,465.6
XS GIS Cut Line= 3
     1630958.221      569038.039     1630499.438      569324.461
     1630405.688      569485.919
#Sta/Elev= 30
       0  580.89    68.8  580.19    88.5  577.96   108.2  573.63     118  570.53
   157.3  555.93   167.2  553.08     177  551.53   285.2  549.15   304.8  549.48
   344.2  551.61   363.8  551.57   383.5  549.46   408.1  542.98     413  541.87
   422.8  541.22   432.7  542.37   452.4  548.81   462.2  551.46   491.7  557.56
   501.5  560.87     531  573.33   540.8   576.4   550.7  578.04   560.5  580.57
   580.2  589.04   629.3  613.82   648.9  622.81   678.4  633.83   727.6  648.34
#Mann= 3 , 0 , 0
       0     .06       0   408.1    .045       0   432.7      .1       0
Bank Sta=408.1,432.7
XS Rating Curve= 0 ,0
Exp/Cntr=0.3,0.1

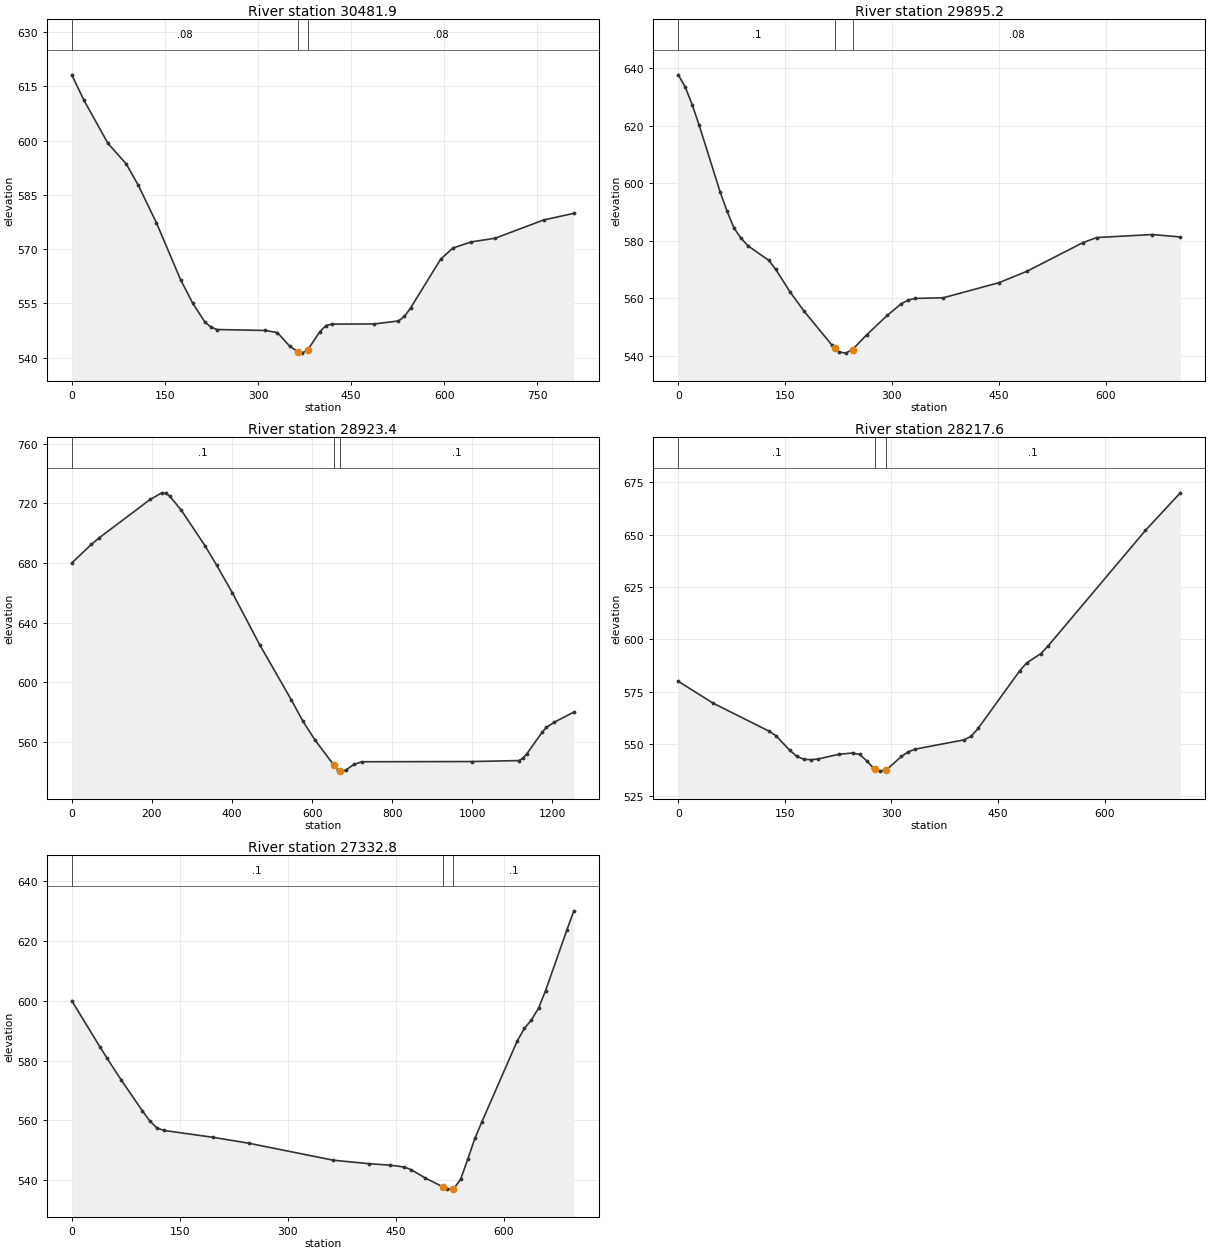
Type RM Length L Ch R = 1 ,30481.9 ,599.1,586.7,574
XS GIS Cut Line= 2
     1630810.652      568630.053     1630107.527      569029.358
#Sta/Elev= 30
       0   618.2    19.5   611.2    58.4  599.21    87.7  593.56   107.2  587.64
   136.4  577.24   175.4  561.49   194.8  555.02   214.3  549.84   224.1  548.42
   233.8  547.75   311.8  547.49   331.2  546.89   350.7   543.2     365  541.47
   370.2  541.22     380  542.09   399.4  547.13   409.2  548.84   418.9  549.25
   487.1  549.29   526.1  550.12   535.8  551.36   545.6   553.7   594.3  567.25
   613.8  570.28     643  571.97     682  573.01   759.9  578.05   808.6  579.89
#Mann= 3 , 0 , 0
       0     .08       0     365    .045       0     380     .08       0
Bank Sta=365,380
XS Rating Curve= 0 ,0
Exp/Cntr=0.3,0.1

Type RM Length L Ch R = 1 ,29895.2 ,1003.5,971.8,939.4
XS GIS Cut Line= 2
     1630384.855      568178.627     1630030.688      568788.002
#Sta/Elev= 30
       0  637.78     9.8  633.56    19.6  627.38    29.4  620.22    58.7   597.1
    68.5  590.32    78.3  584.44    88.1  580.92    97.9  578.25   127.3  573.16
     137  570.01   156.6  562.34   176.2  555.64   215.4  543.78   220.2   542.6
   225.2  541.37   234.9  540.89   244.7  542.15   264.3   547.2   293.7   554.1
   313.2  558.09     323  559.39   332.8  559.94     372  560.16   450.3  565.42
   489.5  569.39   567.8  579.33   587.4  581.13   665.7  582.18   704.8  581.33
#Mann= 3 , 0 , 0
       0      .1       0   220.2    .045       0   244.7     .08       0
Bank Sta=220.2,244.7
XS Rating Curve= 0 ,0
Exp/Cntr=0.3,0.1

Type RM Length L Ch R = 1 ,28923.4 ,693.9,705.8,717.4
XS GIS Cut Line= 3
     1629236.995      567763.961     1629259.332      568164.247
     1629904.811      568721.144
#Sta/Elev= 30
       0     680    48.9  692.47    68.4  696.87   195.6  722.59   224.9  727.06
   234.7  726.84   244.5  724.85   273.8  715.28   332.5  691.63   361.8  678.48
   400.9     660   469.5  624.99   547.9  588.29   577.3  573.78   606.7  561.46
   654.3  544.42   665.5  540.94   669.3  540.73   675.3  540.39   685.1  541.31
   704.7  544.93   724.3  546.68   998.6  546.82  1116.2  547.47    1126  548.98
  1135.8  551.91    1175  566.78  1184.8  569.66  1204.4  573.18  1253.4  579.99
#Mann= 3 , 0 , 0
       0      .1       0   654.3    .045       0   669.3      .1       0
Bank Sta=654.3,669.3
XS Rating Curve= 0 ,0
Exp/Cntr=0.3,0.1

Type RM Length L Ch R = 1 ,28217.6 ,891.9,884.8,877.2
XS GIS Cut Line= 2
     1629024.198      568578.719     1629272.401      569240.336
#Sta/Elev= 30
       0     580    49.1  569.55   127.6  556.24   137.4  554.06     157  547.05
   166.8  544.19   176.7  542.77   186.5  542.56   196.3  542.86   225.7  545.14
   245.4  545.77   255.2  545.07     265  542.14   274.8  538.52   276.9  538.22
   284.6  537.11   291.9  537.88   294.4  538.14   314.1  544.12   323.9  546.36
   333.7  547.63   402.4  552.05   412.2  553.74     422  557.49   480.9  585.16
   490.7  588.88   510.4  593.24   520.2  596.75   657.6  652.09   706.6     670
#Mann= 3 , 0 , 0
       0      .1       0   276.9    .045       0   291.9      .1       0
Bank Sta=276.9,291.9
XS Rating Curve= 0 ,0
Exp/Cntr=0.3,0.1

Type RM Length L Ch R = 1 ,27332.8 ,27342.5,27332.8,27311.6
XS GIS Cut Line= 2
     1628251.853      568997.316     1628701.565      569530.503
#Sta/Elev= 30
       0  599.99    39.3  584.51    49.1  580.75    68.8  573.49    98.2  563.18
   108.1  559.94   117.9  557.58   127.7  556.69   196.5  554.37   245.6  552.42
   363.5  546.73   412.6  545.58   442.1  545.08   461.7  544.47   471.6  543.56
   491.2  540.77   515.3  537.88   520.7  537.22   530.3  537.08   540.3  540.42
   550.2  547.12     560  554.02   569.8  559.58   618.9  586.57   628.8  590.74
   638.6  593.59   648.4  597.47   658.2  603.35   687.7  623.53   697.5     630
#Mann= 3 , 0 , 0
       0      .1       0   515.3    .045       0   530.3      .1       0
Bank Sta=515.3,530.3
XS Rating Curve= 0 ,0
Exp/Cntr=0.3,0.1

Chan Stop Cuts=-1
Use User Specified Reach Order=0
Composite Channel Slope=5